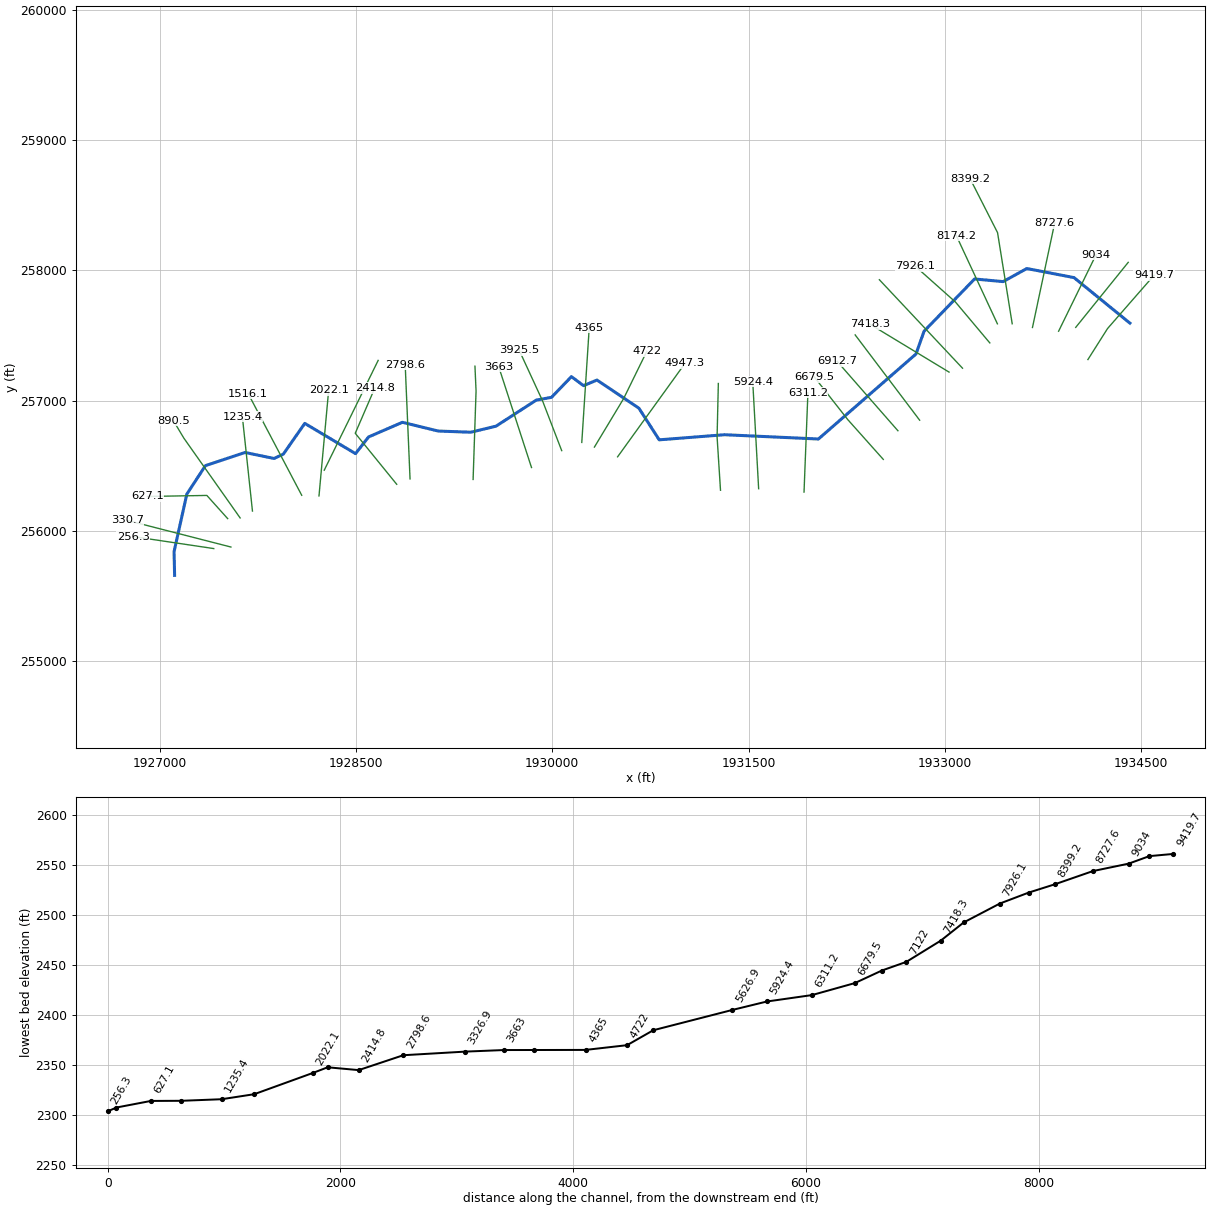
--- LtFkBvrCrk.prj (project) ---

Proj Title=LtFkBvrCrk
Current Plan=p01
Default Exp/Contr=0,0
English Units
Geom File=g01
Flow File=f01
Plan File=p01
BEGIN DESCRIPTION:
END DESCRIPTION:
DSS Export Rating Curves= 0
DSS Export Rating Curve Sorted= 0
DSS Export Volume Flow Curves= 0
DXF OffsetX= 0
DXF OffsetY= 0
DXF ScaleX= 0
DXF ScaleY= 0

--- LtFkBvrCrk.p01 (plan) ---

Plan Title=Floodplain
Program Version=4.00
Geom File=g01
Flow File=f01
K Sum by GR=0
Std Step Tol=0.01
Critical Tol=0.01
Num of Std Step Trials=20
Max Error Tol=0.3
Flow Tol Ratio=0.001
Split Flow NTrial=30
Split Flow Tol=0.02
Split Flow Ratio=0.02
Log Output Level=0
Friction Slope Method=1
Unsteady Friction Slope Method=2
Unsteady Bridges Friction Slope Method=1
Global Log Level=0
CheckData=False
Run HTab=0
Run UNet=0
Run PostProcess=0
UNET Theta=0
UNET Theta Warmup=0
UNET ZTol=0
UNET ZSATol=0
UNET MxIter=0
UNET MaxInSteps=0
UNET DtIC=0
UNET DtMin=0
UNET MaxCRTS=0
UNET WFStab=0
UNET SFStab=0
UNET WFX=0
UNET SFX=0
UNET DSS MLevel=0
UNET DZMax Abort=0
UNET Convert EG Bridges=0
UNET Use Existing IB Tables=0
UNET Froude Limit=0
UNET Froude Power=0
Write IC File=0
Echo Input=False
Echo Output=False
Write Detailed=0

--- LtFkBvrCrk.f01 (steady flow) ---

Flow Title=NFF Regression Equation
Program Version=4.00
Number of Profiles=1
Profile Names=P100yr
River Rch & RM=LtFkBvrCrk,Main      ,9419.7
510.8924
River Rch & RM=LtFkBvrCrk,Main      ,8174.2
566.1804
River Rch & RM=LtFkBvrCrk,Main      ,6311.2
594.3168
River Rch & RM=LtFkBvrCrk,Main      ,5924.4
676.8351
River Rch & RM=LtFkBvrCrk,Main      ,2022.1
732.3577
River Rch & RM=LtFkBvrCrk,Main      ,1516.1
842.2378
River Rch & RM=LtFkBvrCrk,Main      ,256.3
862.3187
Boundary for River Rch & Prof#=LtFkBvrCrk,Main      ,1
Up Type=0
Dn Type=3
Dn Slope=0.029114

--- LtFkBvrCrk.g01 (geometry) ---

Geom Title=USGS 3m DEM
Program Version=4.10

River Reach=LtFkBvrCrk      ,Main
Reach XY= 30
     1934414.203      257594.742     1933986.767       257944.11
     1933626.466      258013.705     1933445.473      257913.343
     1933226.952      257933.581     1932841.039      257532.587
     1932779.145      257357.896     1932033.901      256706.123
     1931317.334      256738.914     1930817.154      256699.845
     1930662.154      256942.122      1930341.73       257158.35
     1930238.828      257115.368     1930146.348      257184.404
     1929993.947      257025.495     1929878.019      257004.656
     1929569.947      256804.483     1929377.414      256758.048
     1929128.181       256767.17     1928854.638      256834.223
     1928596.187      256721.945     1928496.441       256593.94
     1928108.677      256825.915      1927944.67      256589.916
     1927874.012      256556.765     1927652.069       256602.74
     1927349.707      256501.829     1927207.562      256283.737
     1927109.864      255842.174     1927114.012      255659.962

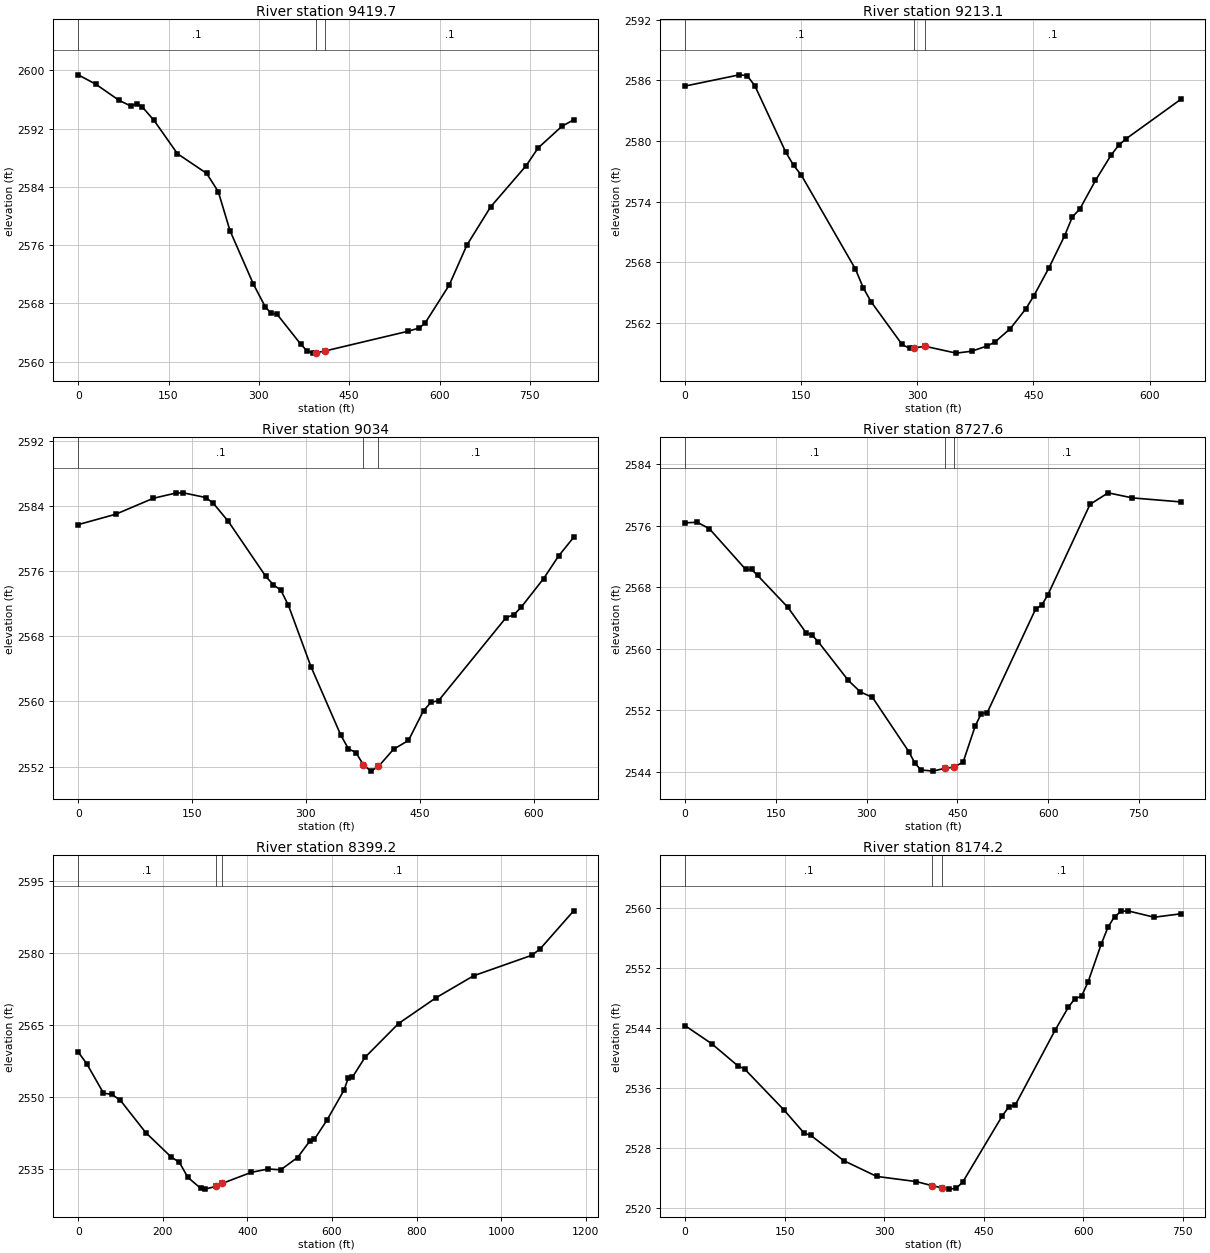
Type RM Length L Ch R = 1 ,9419.7  ,205.3,206.5,207.8
XS GIS Cut Line= 3
     1934093.201      257315.631     1934243.204      257553.371
     1934598.735      257961.898
#Sta/Elev= 30
       0  2599.4    29.1 2598.12    67.8  2595.9    87.2 2595.12    96.9 2595.44
   106.6 2594.98     126 2593.13   164.8 2588.57   213.2 2585.87   232.6 2583.36
     252 2578.01     291 2570.64   310.6 2567.54   320.5 2566.65   330.3 2566.51
   369.7 2562.39   379.6 2561.52   389.4 2561.18   394.7 2561.23   409.7 2561.47
     547 2564.17   566.7 2564.64   576.5 2565.37   615.9  2570.5   645.4 2576.01
   684.8 2581.26   743.9 2586.93   763.6 2589.35     803 2592.32   822.7 2593.22
#Mann= 3 , 0 , 0
       0      .1       0   394.7    .045       0   409.7      .1       0
Bank Sta=394.7,409.7
XS Rating Curve= 0 ,0
Exp/Cntr=0.3,0.1

Type RM Length L Ch R = 1 ,9213.1  ,174,178.9,183.8
XS GIS Cut Line= 2
     1934000.024      257562.304     1934401.212      258061.135
#Sta/Elev= 30
       0 2585.45      70 2586.56      80 2586.48      90 2585.48     130 2578.89
     140  2577.6     150 2576.63     220 2567.31     230 2565.47     240  2564.1
   280.1 2559.86   290.1 2559.45   295.4 2559.52   310.4 2559.66   350.1 2558.99
   370.1 2559.18   390.1  2559.7   400.1 2560.08   420.1 2561.42   440.1 2563.38
   450.1 2564.62   470.1 2567.46   490.1  2570.6   500.1 2572.46   510.1  2573.3
   530.1  2576.1   550.1 2578.59   560.1 2579.59   570.1 2580.25   640.1 2584.12
#Mann= 3 , 0 , 0
       0      .1       0   295.4    .045       0   310.4      .1       0
Bank Sta=295.4,310.4
XS Rating Curve= 0 ,0
Exp/Cntr=0.3,0.1

Type RM Length L Ch R = 1 ,9034    ,300.9,306.4,312
XS GIS Cut Line= 2
     1933869.244      257532.835     1934155.467       258119.42
#Sta/Elev= 30
       0 2581.71    49.4 2582.98    98.9 2584.94   128.6 2585.58   138.4 2585.61
   168.1 2585.03     178 2584.33   197.8  2582.1   247.2 2575.34   257.1 2574.33
     267 2573.65   276.9 2571.81   306.6 2564.28   346.1 2555.84     356 2554.19
   365.9 2553.73   375.8 2552.21   385.7 2551.45   395.6 2552.03   415.4 2554.13
   435.1 2555.22   454.9 2558.87   464.8 2559.89   474.7  2560.1   563.7  2570.3
   573.6 2570.62   583.5 2571.56   613.1 2575.08   632.9 2577.86   652.7 2580.15
#Mann= 3 , 0 , 0
       0      .1       0   375.8    .045       0   395.6      .1       0
Bank Sta=375.8,395.6
XS Rating Curve= 0 ,0
Exp/Cntr=0.3,0.1

Type RM Length L Ch R = 1 ,8727.6  ,319.5,328,336.5
XS GIS Cut Line= 3
     1933669.575      257561.504     1933754.333      257962.136
     1933839.091      258362.769
#Sta/Elev= 30
       0 2576.35      20 2576.42      40 2575.58    99.9  2570.3   109.9 2570.28
   119.8  2569.5   169.8 2565.36   199.8 2562.06   209.7 2561.74   219.7 2560.91
   269.7 2555.85   289.6 2554.36   309.6 2553.65   369.6  2546.6   379.5 2545.13
   389.5 2544.22   409.5 2544.06   428.7 2544.42   443.7 2544.57   459.4 2545.22
   479.4 2549.92   489.4 2551.53   499.4 2551.68   579.3 2565.14   589.3 2565.64
   599.3 2566.95   669.2 2578.75   699.2 2580.25   739.1 2579.59     819 2579.07
#Mann= 3 , 0 , 0
       0      .1       0   428.7    .045       0   443.7      .1       0
Bank Sta=428.7,443.7
XS Rating Curve= 0 ,0
Exp/Cntr=0.3,0.1

Type RM Length L Ch R = 1 ,8399.2  ,217,224.1,231.2
XS GIS Cut Line= 3
     1933514.675       257590.01     1933402.621      258289.235
     1933193.183      258702.451
#Sta/Elev= 30
       0 2559.42      20 2557.02    59.8 2550.85    79.8 2550.59    99.7 2549.36
   159.6 2542.63   219.4 2537.57   239.4  2536.4   259.3 2533.27   289.2 2531.04
   299.2 2530.83   325.5 2531.39   340.5 2532.02   408.9 2534.32   448.8 2535.03
   478.8 2534.86   518.6 2537.42   548.6 2540.97   558.5 2541.23   588.5 2545.27
   628.4 2551.46   638.3 2553.96   648.3 2554.17   678.2 2558.33   757.4 2565.37
   846.1 2570.75   934.8 2575.33  1072.8 2579.62  1092.6 2580.98  1171.4 2588.88
#Mann= 3 , 0 , 0
       0      .1       0   325.5    .045       0   340.5      .1       0
Bank Sta=325.5,340.5
XS Rating Curve= 0 ,0
Exp/Cntr=0.3,0.1

Type RM Length L Ch R = 1 ,8174.2  ,241.7,248.5,257.1
XS GIS Cut Line= 2
     1933401.427      257589.899      1933087.27      258267.035
#Sta/Elev= 30
       0 2544.31    39.8 2541.93    79.6 2538.96    89.6 2538.55   149.3 2533.06
   179.2 2530.02   189.1 2529.73   238.9 2526.36   288.6 2524.26   348.4 2523.57
   372.1 2523.03   387.1 2522.73   398.1 2522.57   408.1 2522.68     418 2523.48
   477.7 2532.31   487.7 2533.52   497.6  2533.8   557.4 2543.72   577.3 2546.77
   587.2 2547.92   597.2 2548.24   607.1 2550.15     627 2555.21     637 2557.41
   646.9 2558.84   656.9 2559.52   666.8  2559.6   706.6 2558.75   746.5  2559.2
#Mann= 3 , 0 , 0
       0      .1       0   372.1    .045       0   387.1      .1       0
Bank Sta=372.1,387.1
XS Rating Curve= 0 ,0
Exp/Cntr=0.3,0.1

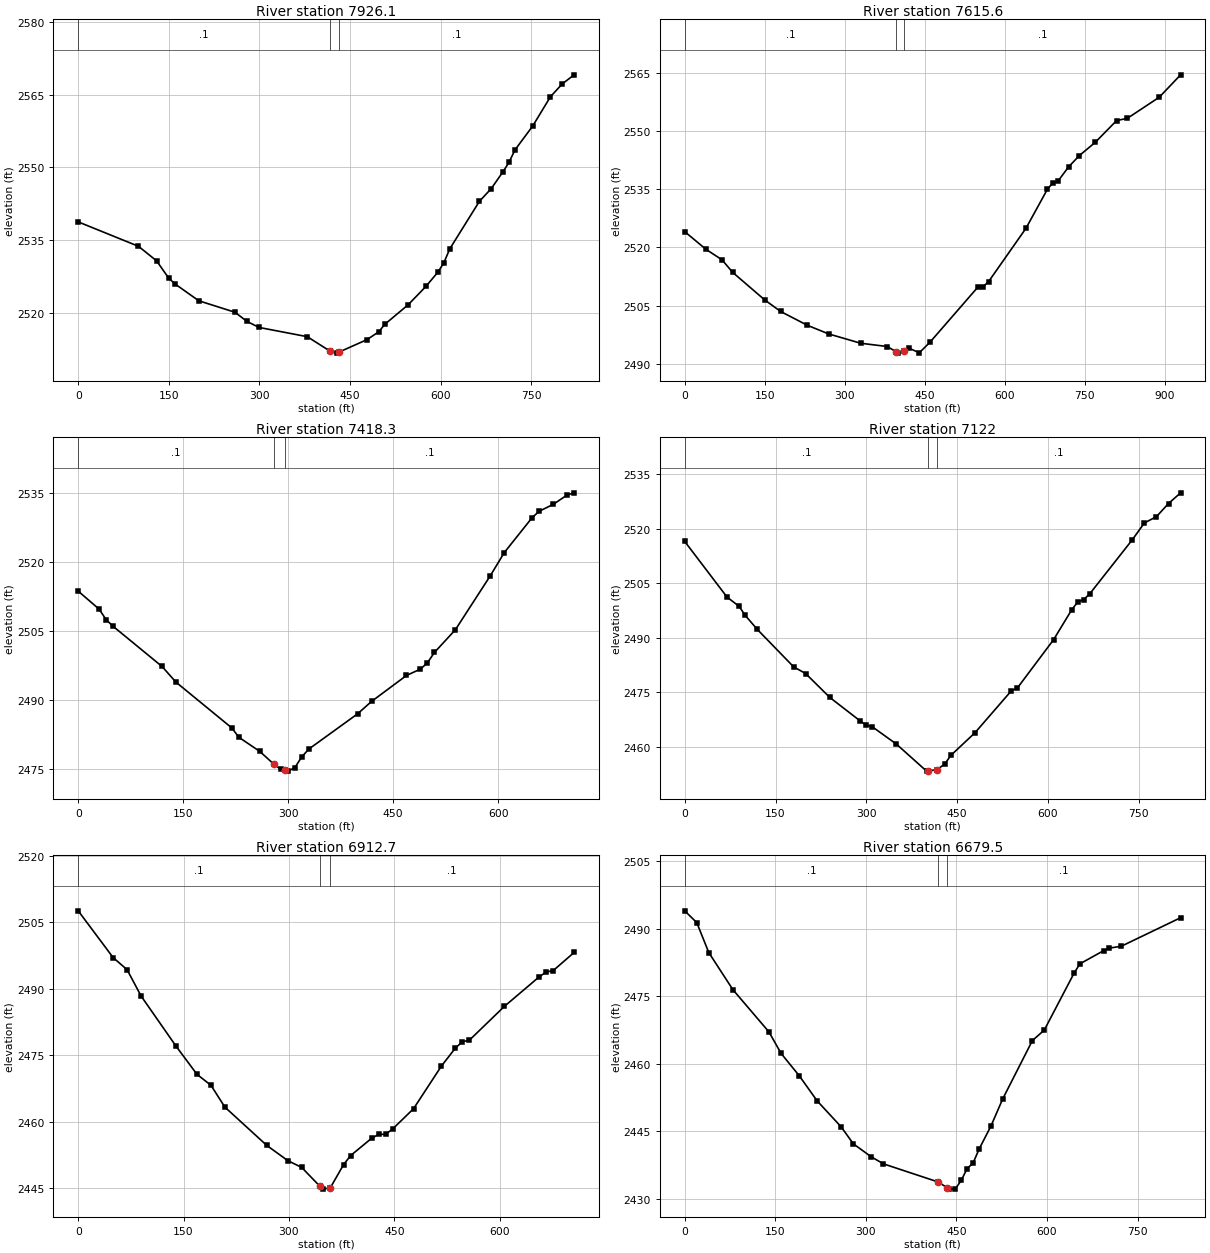
Type RM Length L Ch R = 1 ,7926.1  ,310.8,310.5,308.4
XS GIS Cut Line= 3
     1933343.454      257443.105      1933080.77       257756.98
     1932773.631       258031.49
#Sta/Elev= 30
       0 2538.75    99.8  2533.7   129.8 2530.69   149.7 2527.14   159.7 2525.97
   199.6 2522.44   259.6 2520.06   279.5 2518.16   299.5 2516.92   379.3 2515.01
   416.6 2512.05   428.9 2511.61   431.6 2511.81     478 2514.39   497.6 2516.01
   507.4 2517.54   546.6 2521.64     576 2525.44   595.6 2528.36   605.4 2530.28
   615.3 2533.18   664.3    2543   683.9 2545.63   703.5 2549.14   713.3 2551.06
   723.2 2553.63   752.6 2558.58     782 2564.64   801.6  2567.3   821.2 2569.16
#Mann= 3 , 0 , 0
       0      .1       0   416.6    .045       0   431.6      .1       0
Bank Sta=416.6,431.6
XS Rating Curve= 0 ,0
Exp/Cntr=0.3,0.1

Type RM Length L Ch R = 1 ,7615.6  ,190.1,197.3,204.4
XS GIS Cut Line= 2
     1933134.948      257249.178     1932499.773      257927.671
#Sta/Elev= 30
       0 2524.05      40 2519.48      70 2516.78    89.9 2513.55   149.9 2506.45
   179.9 2503.46   229.8 2499.91   269.8 2497.68   329.8 2495.28   379.8 2494.43
   395.8 2493.11   399.8 2492.73   410.8 2493.16   419.7 2494.05   439.7 2492.82
   459.7 2495.54   549.6 2509.77   559.6 2509.89   569.6 2511.18   639.6 2524.91
   679.6 2534.93   689.6 2536.56   699.6 2537.07   719.5 2540.74   739.5 2543.63
   769.5 2547.07   809.5 2552.68   829.5 2553.24   889.4 2558.69   929.4 2564.46
#Mann= 3 , 0 , 0
       0      .1       0   395.8    .045       0   410.8      .1       0
Bank Sta=395.8,410.8
XS Rating Curve= 0 ,0
Exp/Cntr=0.3,0.1

Type RM Length L Ch R = 1 ,7418.3  ,304.9,296.3,287.7
XS GIS Cut Line= 2
     1933031.859      257219.402     1932426.187      257587.334
#Sta/Elev= 30
       0  2513.6    29.9 2509.69    39.9 2507.41    49.9 2505.96   119.8 2497.25
   139.7 2493.85   219.6  2483.9   229.6 2481.88   259.5 2478.82   279.9    2476
   289.5 2474.92   294.9 2474.71   299.4 2474.54   309.4 2475.26   319.4 2477.62
   329.4 2479.31   399.2 2486.97   419.2 2489.67   469.1  2495.3   489.1 2496.69
   499.1 2498.06     509 2500.29     539 2505.23   588.9 2516.95   608.9 2521.98
   648.8 2529.58   658.8 2530.95   678.7 2532.42   698.7 2534.47   708.7 2534.94
#Mann= 3 , 0 , 0
       0      .1       0   279.9    .045       0   294.9      .1       0
Bank Sta=279.9,294.9
XS Rating Curve= 0 ,0
Exp/Cntr=0.3,0.1

Type RM Length L Ch R = 1 ,7122    ,207.6,209.2,210.8
XS GIS Cut Line= 3
     1932807.347      256850.466     1932560.972      257177.559
     1932314.598      257504.652
#Sta/Elev= 30
       0 2516.53    69.9 2501.21    89.9 2498.66    99.9 2496.18   119.8 2492.33
   179.8 2482.03   199.8 2480.16   239.7 2473.59   289.6 2467.16   299.6 2465.96
   309.6 2465.55   349.6 2460.76   399.5 2453.32     402 2453.35     417 2453.76
   429.5 2455.28   439.5 2457.64   479.4 2463.88   539.3 2475.39   549.3 2476.17
   609.3 2489.51   639.2 2497.72   649.2 2499.88   659.2 2500.54   669.2 2502.16
   739.1 2516.95   759.1  2521.6     779 2523.32     799 2526.95     819 2529.89
#Mann= 3 , 0 , 0
       0      .1       0     402    .045       0     417      .1       0
Bank Sta=402,417
XS Rating Curve= 0 ,0
Exp/Cntr=0.3,0.1

Type RM Length L Ch R = 1 ,6912.7  ,234.2,233.2,232.1
XS GIS Cut Line= 2
     1932641.285      256769.393     1932177.125      257301.479
#Sta/Elev= 30
       0 2507.61    49.7 2497.05    69.6 2494.31    89.5 2488.37   139.2 2477.05
   169.1 2470.67     189  2468.2   208.8 2463.27   268.5 2454.61   298.4 2451.18
   318.2 2449.64   343.9 2445.42   348.1 2444.74   358.9 2445.03   377.9  2450.3
   387.8 2452.31   417.7 2456.22   427.6  2457.1   437.6 2457.13   447.5  2458.3
   477.4  2462.9   517.1 2472.54     537  2476.6     547 2478.05   556.9 2478.38
   606.6    2486   656.4 2492.71   666.3 2493.79   676.2  2494.1   706.1 2498.21
#Mann= 3 , 0 , 0
       0      .1       0   343.9    .045       0   358.9      .1       0
Bank Sta=343.9,358.9
XS Rating Curve= 0 ,0
Exp/Cntr=0.3,0.1

Type RM Length L Ch R = 1 ,6679.5  ,385.8,368.3,350.8
XS GIS Cut Line= 3
     1932529.425      256549.711     1932257.716      256855.392
     1932003.676      257180.298
#Sta/Elev= 30
       0 2493.95      20 2491.34    39.9 2484.69    79.8 2476.45   139.6 2467.06
   159.6  2462.3   189.5 2457.37   219.4 2451.75   259.4 2445.94   279.3 2442.21
   309.2 2439.31   329.2 2437.76   419.8 2433.74   434.8 2432.46   438.4 2432.15
   448.3  2432.2   458.1 2434.11   467.9 2436.72   477.7 2437.95   487.5 2441.01
   507.2 2446.14   526.8  2452.2   575.9 2465.14   595.6 2467.47   644.7 2480.05
   654.5 2482.17   693.8  2485.1   703.6 2485.67   723.2 2486.09   821.4 2492.42
#Mann= 3 , 0 , 0
       0      .1       0   419.8    .045       0   434.8      .1       0
Bank Sta=419.8,434.8
XS Rating Curve= 0 ,0
Exp/Cntr=0.3,0.1

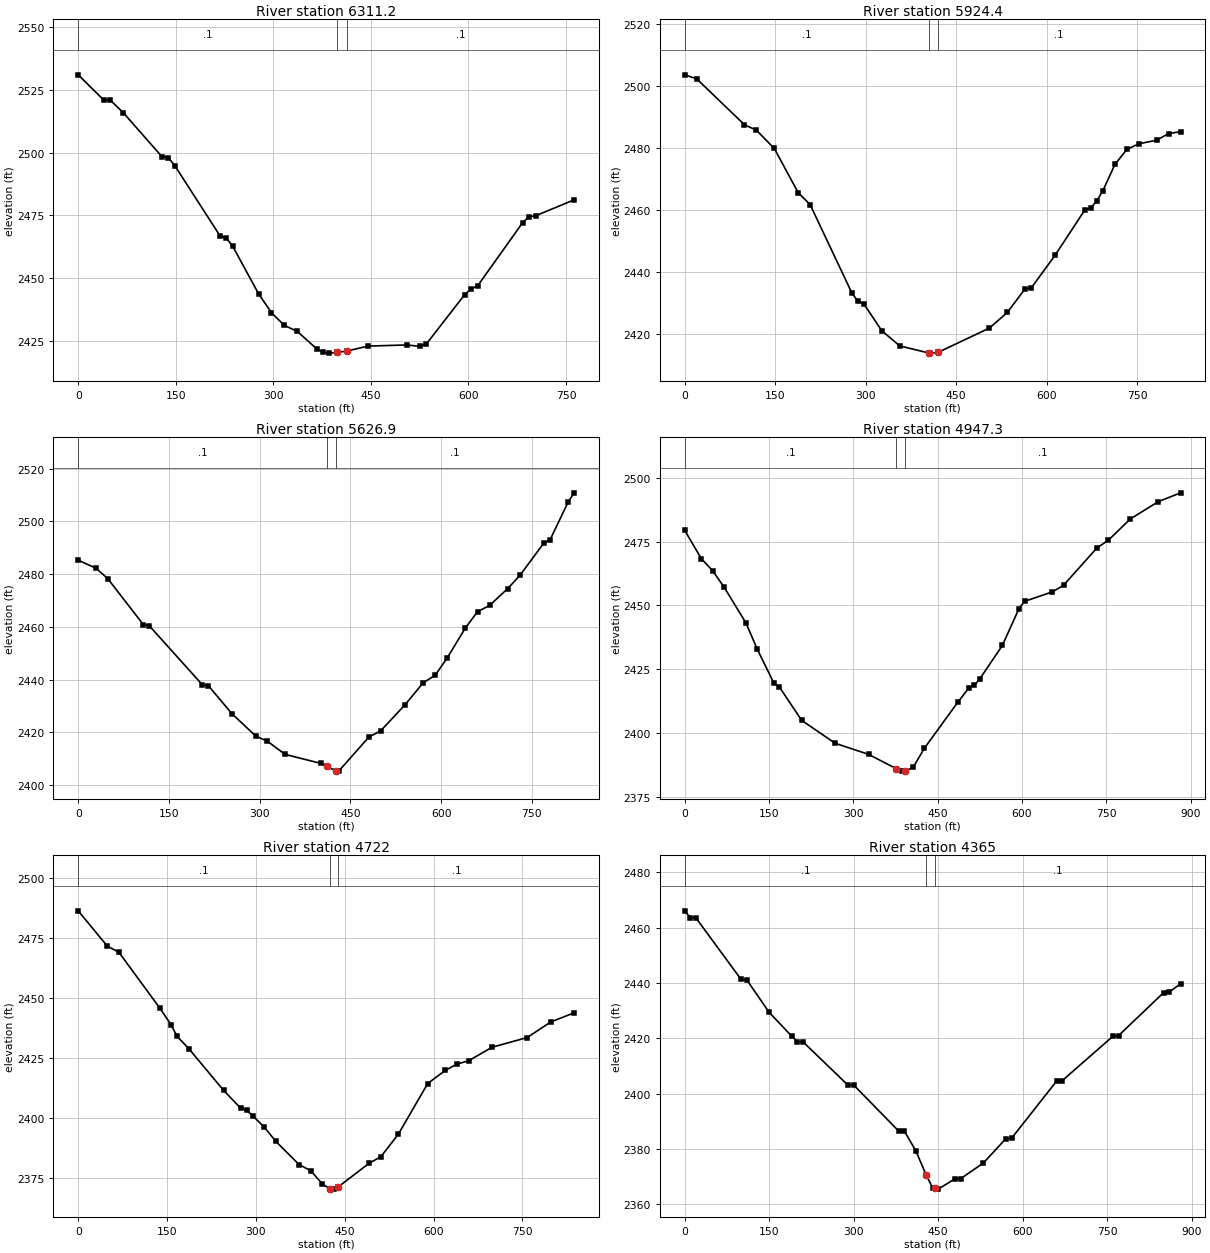
Type RM Length L Ch R = 1 ,6311.2  ,384.7,386.8,389
XS GIS Cut Line= 2
     1931923.827      256298.963     1931953.536      257060.908
#Sta/Elev= 30
       0 2530.95    39.6 2520.83    49.5  2520.8    69.3 2515.88   128.7 2498.38
   138.6 2497.98   148.5  2494.8   217.9 2466.92   227.8 2465.97   237.7 2462.64
   277.3  2443.8   297.1 2436.29   316.9  2431.2   336.7 2428.86   366.4 2421.95
   376.3  2420.5   386.2 2420.18   397.9 2420.47   412.9    2421   445.6 2422.98
     505 2423.43   524.8 2422.89   534.8 2423.67   594.2 2443.47   604.1 2445.75
     614 2446.92   683.3 2472.11   693.2  2474.5   703.1 2474.84   762.5 2481.19
#Mann= 3 , 0 , 0
       0      .1       0   397.9    .045       0   412.9      .1       0
Bank Sta=397.9,412.9
XS Rating Curve= 0 ,0
Exp/Cntr=0.3,0.1

Type RM Length L Ch R = 1 ,5924.4  ,297.9,297.5,295.7
XS GIS Cut Line= 2
     1931577.017      256324.803     1931531.829      257145.816
#Sta/Elev= 30
       0 2503.63    19.8 2502.36    99.1 2487.51   118.9 2485.76   148.6 2479.85
   188.2 2465.58     208 2461.74   277.4 2433.12   287.3 2430.51   297.2 2429.64
   326.9 2420.99   356.6 2416.11   404.7 2413.83   406.2 2413.78   419.7 2413.99
   505.2 2421.86     535 2426.92   564.7 2434.63   574.6 2434.81   614.2 2445.39
   663.8 2460.09   673.7 2460.68   683.6 2463.05   693.5 2466.26   713.3 2474.69
   733.1 2479.53   752.9 2481.36   782.6 2482.52   802.4 2484.68   822.3 2485.26
#Mann= 3 , 0 , 0
       0      .1       0   404.7    .045       0   419.7      .1       0
Bank Sta=404.7,419.7
XS Rating Curve= 0 ,0
Exp/Cntr=0.3,0.1

Type RM Length L Ch R = 1 ,5626.9  ,694.5,679.5,665.9
XS GIS Cut Line= 3
     1931285.602      256312.898     1931259.431       256722.76
     1931269.052      257131.946
#Sta/Elev= 30
       0 2485.32    29.3 2482.28    48.9 2478.31   107.6 2460.91   117.3 2460.52
   205.4 2438.04   215.1 2437.76   254.2 2427.11   293.4 2418.66   312.9 2416.66
   342.2 2411.67   400.9 2408.29   410.6 2407.11   425.6 2405.51   430.7 2405.34
   480.6 2418.26   500.5  2420.7   540.5 2430.54   570.4 2438.83   590.4 2441.73
   610.4 2448.38   640.3 2459.66   660.3  2465.8   680.2 2468.17   710.2 2474.56
   730.2 2479.52   770.1  2491.9   780.1    2493     810 2507.34     820 2510.86
#Mann= 3 , 0 , 0
       0      .1       0   410.6    .045       0   425.6      .1       0
Bank Sta=410.6,425.6
XS Rating Curve= 0 ,0
Exp/Cntr=0.3,0.1

Type RM Length L Ch R = 1 ,4947.3  ,223.4,225.3,229.1
XS GIS Cut Line= 2
      1930499.14      256569.268     1931013.749      257285.574
#Sta/Elev= 30
       0 2479.49    29.7 2468.33    49.6 2463.67    69.4 2457.43     109 2443.17
   128.8    2433   158.6 2419.59   168.5 2418.03   208.1 2404.96   267.6 2395.99
     327 2391.65   376.5 2386.01   386.5 2385.07   391.5 2385.08   406.3 2386.53
   426.1 2393.97   485.6 2412.04   505.4 2417.65   515.3 2418.71   525.2 2421.34
   564.9 2434.32   594.6  2448.8   604.5 2451.64   654.1 2455.35   673.9 2457.96
   733.3  2472.6   753.2 2475.54   792.8 2483.97   842.4 2490.73     882 2494.17
#Mann= 3 , 0 , 0
       0      .1       0   376.5    .045       0   391.5      .1       0
Bank Sta=376.5,391.5
XS Rating Curve= 0 ,0
Exp/Cntr=0.3,0.1

Type RM Length L Ch R = 1 ,4722    ,346,356.9,366
XS GIS Cut Line= 3
     1930322.024      256644.225     1930544.323      257014.435
     1930722.454      257378.782
#Sta/Elev= 30
       0 2486.28    49.1 2471.56    68.7 2468.99   137.4 2445.82     157 2438.66
   166.8 2433.91   186.5 2428.83   245.4 2411.38   274.8  2403.8   284.6 2403.04
   294.4 2400.83     314 2396.05   333.7 2390.07   372.9 2380.41   392.6 2377.83
   412.2 2372.31   424.3 2370.37   431.8 2370.15   439.3 2371.13   491.2 2380.94
     511 2383.66   540.6  2393.1   590.1 2414.21   619.8 2419.69   639.6 2422.32
   659.3 2423.73   698.9 2429.36   758.2 2433.42   797.8  2439.9   837.4 2443.72
#Mann= 3 , 0 , 0
       0      .1       0   424.3    .045       0   439.3      .1       0
Bank Sta=424.3,439.3
XS Rating Curve= 0 ,0
Exp/Cntr=0.3,0.1

Type RM Length L Ch R = 1 ,4365    ,428.9,439.2,451.4
XS GIS Cut Line= 2
     1930225.555      256679.756     1930282.349      257558.525
#Sta/Elev= 30
       0 2466.08      10 2463.64      20 2463.51   100.1 2441.29   110.1 2441.16
   150.1 2429.32   190.1 2420.75   200.1 2418.74   210.1 2418.69   290.2 2402.97
   300.2 2403.04   380.3 2386.37   390.3 2386.33   410.3 2379.32     429 2370.46
   440.3 2365.91     444 2365.73   450.3 2365.42   480.3 2369.21   490.3 2369.24
   530.4 2374.87   570.4 2383.68   580.4  2383.8   660.4  2404.5   670.5 2404.68
   760.5 2420.73   770.5 2420.97   850.6 2436.52   860.6 2436.75   880.6 2439.71
#Mann= 3 , 0 , 0
       0      .1       0     429    .045       0     444      .1       0
Bank Sta=429,444
XS Rating Curve= 0 ,0
Exp/Cntr=0.3,0.1

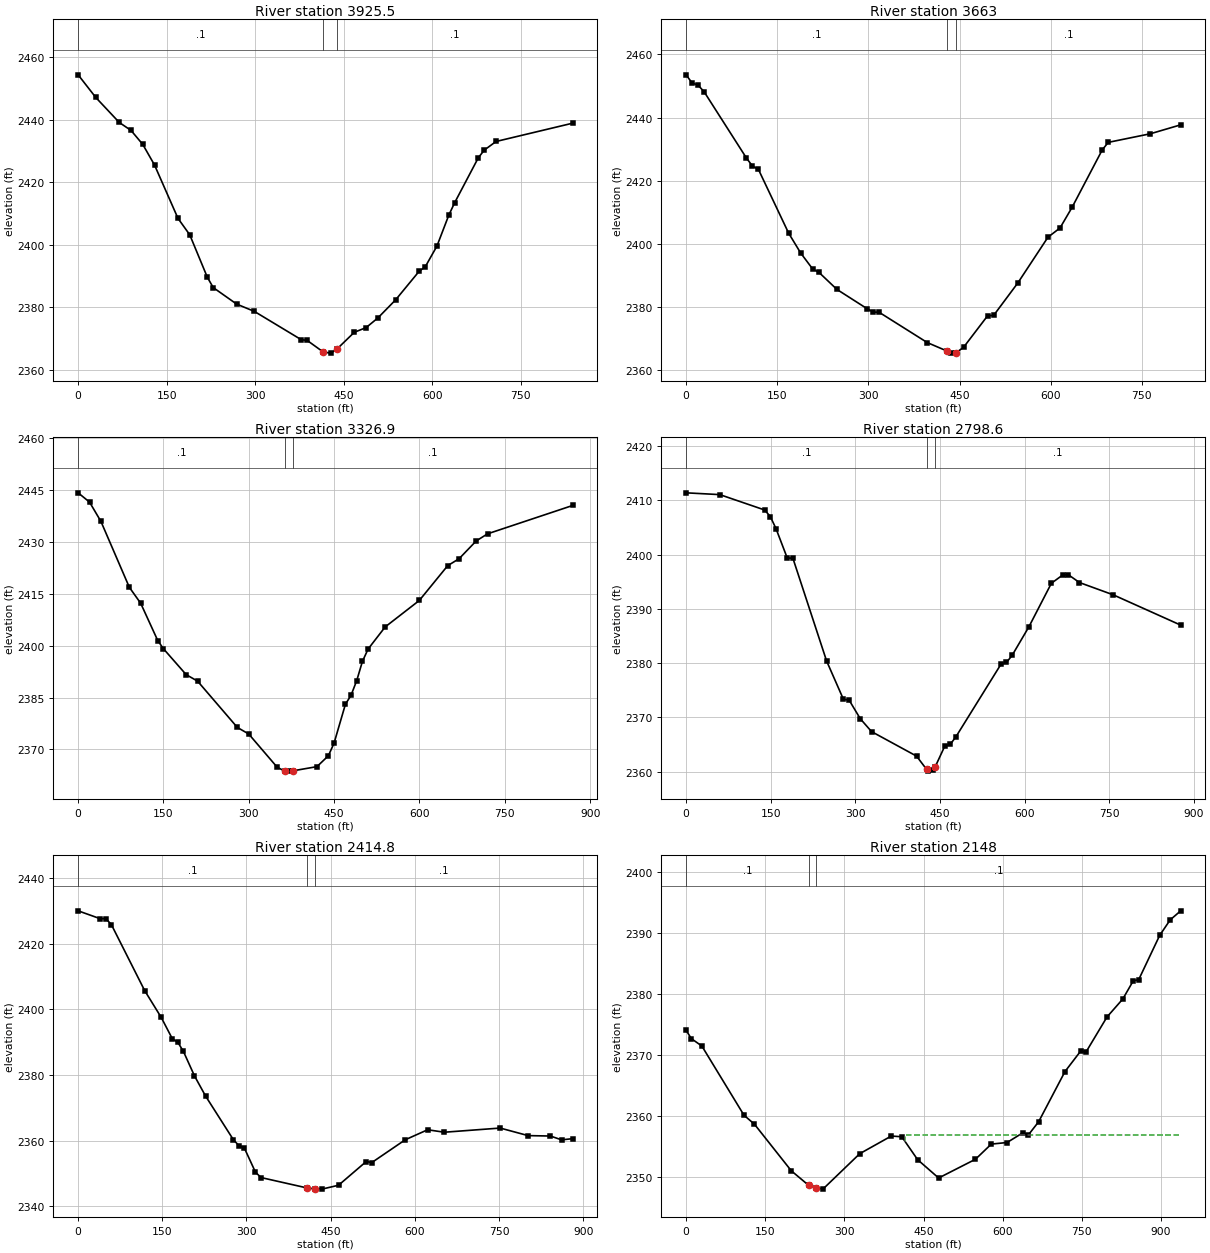
Type RM Length L Ch R = 1 ,3925.5  ,261.4,262.6,259.6
XS GIS Cut Line= 3
     1930072.017      256616.817     1929926.039      256997.777
     1929746.315      257388.708
#Sta/Elev= 30
       0 2454.34    29.8 2447.12    69.6 2439.12    89.6 2436.56   109.5 2432.09
   129.4 2425.51   169.2 2408.43   189.1 2403.19   218.9 2389.61   228.9  2386.3
   268.7    2381   298.5 2378.69   378.1 2369.63   388.1  2369.4   415.5 2365.67
     428 2365.33     438 2366.52     468    2372     488 2373.49     508 2376.59
     538 2382.36   578.1 2391.56   588.1 2392.89   608.1 2399.59   628.1 2409.44
   638.1 2413.45   678.1 2427.79   688.1 2430.24   708.2 2433.02   838.2 2438.88
#Mann= 3 , 0 , 0
       0      .1       0   415.5    .045       0     438      .1       0
Bank Sta=415.5,438
XS Rating Curve= 0 ,0
Exp/Cntr=0.3,0.1

Type RM Length L Ch R = 1 ,3663    ,343.6,336.1,329
XS GIS Cut Line= 2
     1929841.199       256487.55     1929590.281      257261.856
#Sta/Elev= 30
       0 2453.55     9.9 2450.96    19.8 2450.27    29.8 2448.14    99.3 2427.17
   109.2 2424.62   119.1 2423.53   168.8 2403.33   188.6 2397.04   208.4 2391.95
   218.4 2390.95   248.2  2385.5   297.8 2379.39   307.7  2378.3   317.6 2378.26
     397 2368.63     429 2365.99   436.8 2365.29     444 2365.37   456.6 2367.12
   496.3 2377.15   506.2 2377.26   545.9 2387.53   595.6 2402.06   615.4 2404.98
   635.3 2411.54   684.9 2429.75   694.8 2432.13   764.3 2434.87     814 2437.69
#Mann= 3 , 0 , 0
       0      .1       0     429    .045       0     444      .1       0
Bank Sta=429,444
XS Rating Curve= 0 ,0
Exp/Cntr=0.3,0.1

Type RM Length L Ch R = 1 ,3326.9  ,526.5,528.2,530
XS GIS Cut Line= 3
     1929394.994      256395.801     1929417.636       257075.06
     1929409.145      257264.686
#Sta/Elev= 30
       0 2444.24      20 2441.56      40 2435.98      90 2416.89   109.9 2412.29
   139.9  2401.5   149.9 2399.12   189.9 2391.62   209.9 2389.75   279.8 2376.35
   299.8 2374.45   349.8 2364.84   362.9 2363.72   369.8  2363.7   377.9  2363.8
   419.8    2365   439.8 2368.14   449.8 2371.78   469.8 2383.05   479.7 2385.66
   489.7 2389.91   499.7 2395.46   509.7 2399.04   539.7 2405.43   599.7 2413.09
   649.6 2423.16   669.6 2425.17   699.6  2430.3   719.6 2432.37   869.4 2440.59
#Mann= 3 , 0 , 0
       0      .1       0   362.9    .045       0   377.9      .1       0
Bank Sta=362.9,377.9
XS Rating Curve= 0 ,0
Exp/Cntr=0.3,0.1

Type RM Length L Ch R = 1 ,2798.6  ,369.5,383.8,398.2
XS GIS Cut Line= 2
     1928913.134      256399.664     1928876.088       257275.67
#Sta/Elev= 30
       0 2411.39    59.8 2411.06   139.5 2408.22   149.4 2406.99   159.4  2404.8
   179.3 2399.39   189.3 2399.36   249.1 2380.41     279 2373.33   288.9 2373.22
   308.9 2369.76   328.8  2367.4   408.5 2362.89   426.4 2360.44   428.4 2360.12
   438.4 2360.26   441.4 2360.87   458.3 2364.66   468.3 2365.06   478.2 2366.42
     558 2379.78   567.9 2380.14   577.9 2381.43   607.8 2386.72   647.6 2394.73
   667.6 2396.25   677.5 2396.31   697.4 2394.86   757.2  2392.6   876.8 2387.02
#Mann= 3 , 0 , 0
       0      .1       0   426.4    .045       0   441.4      .1       0
Bank Sta=426.4,441.4
XS Rating Curve= 0 ,0
Exp/Cntr=0.3,0.1

Type RM Length L Ch R = 1 ,2414.8  ,293.1,266.7,239.8
XS GIS Cut Line= 3
     1928811.109      256358.848     1928494.312      256750.112
     1928643.962      257097.171
#Sta/Elev= 30
       0 2430.01    39.5  2427.6    49.4 2427.64    59.2 2425.82   118.5 2405.73
   148.1 2397.53   167.8 2391.06   177.7 2389.95   187.6 2387.19   207.3 2379.74
     227 2373.62   276.4 2360.36   286.3 2358.52   296.1  2357.8   315.9 2350.44
   325.8 2348.78   407.1 2345.64   422.1 2345.36   434.3 2345.25     464 2346.43
   513.4 2353.66   523.3 2353.34     583 2360.29   622.8 2363.33   652.6 2362.58
   752.1 2363.85   801.8 2361.55   841.6 2361.42   861.5 2360.26   881.4 2360.62
#Mann= 3 , 0 , 0
       0      .1       0   407.1    .045       0   422.1      .1       0
Bank Sta=407.1,422.1
XS Rating Curve= 0 ,0
Exp/Cntr=0.3,0.1

Type RM Length L Ch R = 1 ,2148    ,118.3,125.9,133.4
XS GIS Cut Line= 2
       1928257.5      256466.933     1928669.434      257308.909
#Sta/Elev= 30
       0 2374.06      10 2372.69    29.9 2371.48   109.7 2360.16   129.6 2358.68
   199.4 2351.06     232  2348.7     247 2348.25   259.3 2348.06   329.1 2353.86
   388.9 2356.75   408.8 2356.63   438.8 2352.88   478.6 2349.88   548.4 2352.95
   578.4 2355.43   608.3 2355.69   638.2 2357.28   648.2 2356.88   668.1 2359.09
     718  2367.3   747.9 2370.67   757.8 2370.49   797.7 2376.24   827.6 2379.18
   847.6 2382.18   857.6 2382.32   897.5 2389.59   917.4 2392.13   937.3 2393.61
#Mann= 3 , 0 , 0
       0      .1       0     232    .045       0     247      .1       0
#XS Ineff= 2 , 0
                          415.27         2356.89
Permanent Ineff=
       F       F
Bank Sta=232,247
XS Rating Curve= 0 ,0
Exp/Cntr=0.3,0.1

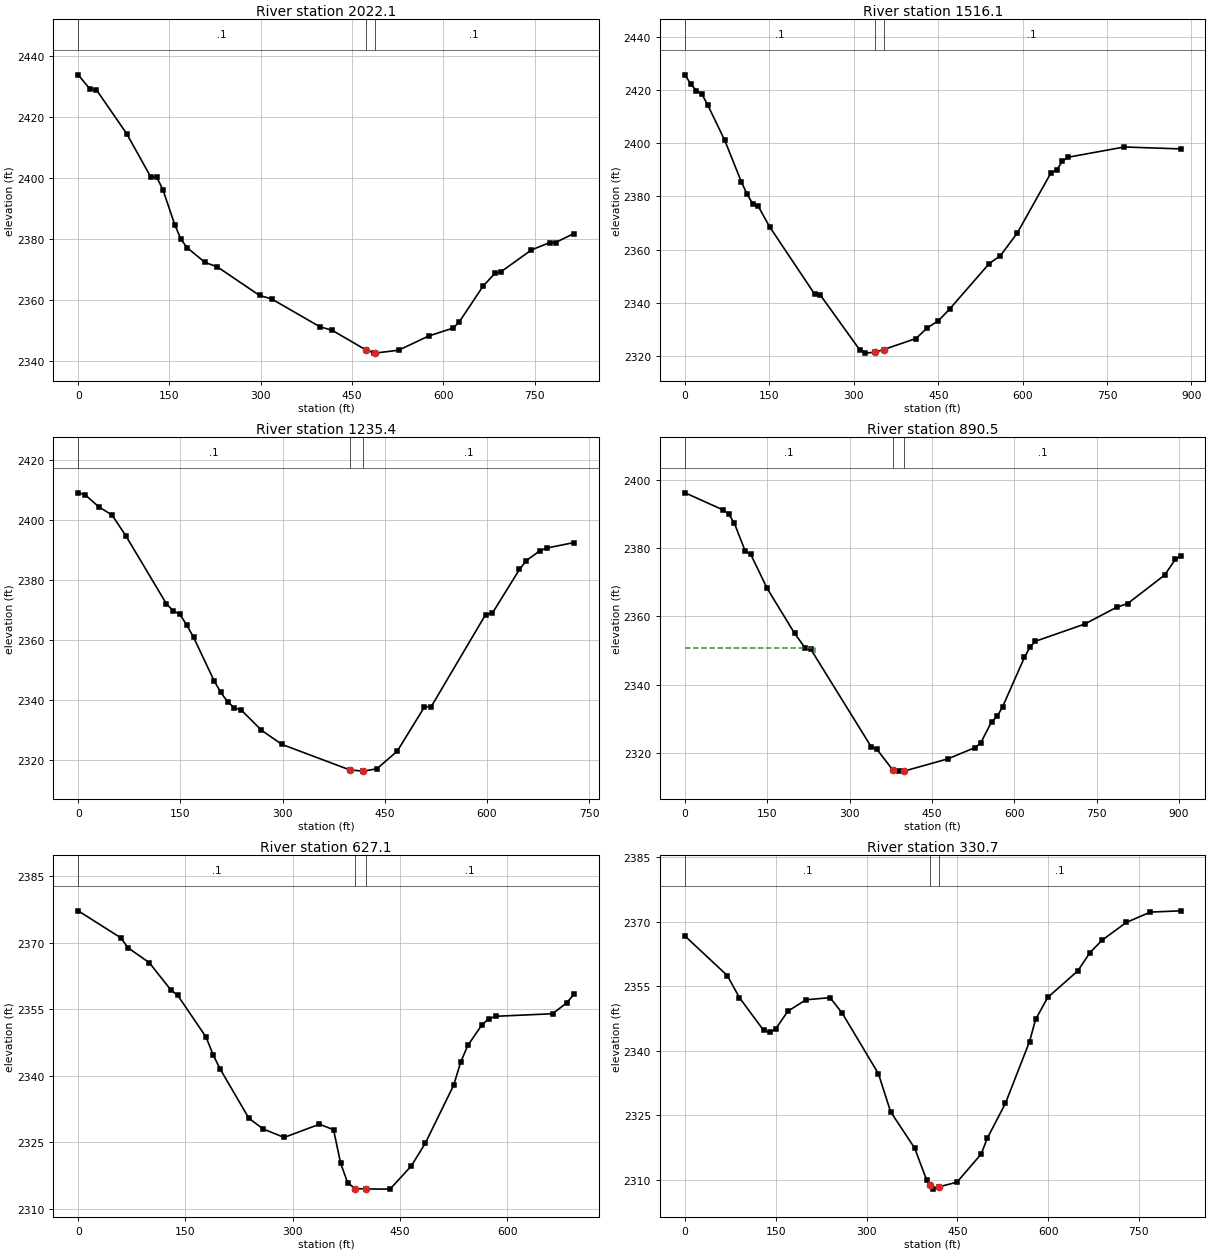
Type RM Length L Ch R = 1 ,2022.1  ,493.1,505.6,518.2
XS GIS Cut Line= 2
     1928217.376       256269.55     1928291.198       257080.72
#Sta/Elev= 30
       0 2433.72    19.9 2428.91    29.8 2428.85    79.5 2414.47   119.2 2400.25
   129.1 2400.13   139.1 2396.11   158.9 2384.47   168.9 2379.81   178.8 2377.07
   208.6 2372.18   228.5 2370.77     298 2361.39   317.9 2360.23   397.3  2351.1
   417.2 2349.97   472.3 2343.58   486.7 2342.46   487.3 2342.46   526.5 2343.41
   576.1 2348.08   615.9 2350.65   625.8 2352.55   665.5 2364.45   685.4  2368.7
   695.3  2369.2     745  2376.3   774.8  2378.7   784.7 2378.73   814.5 2381.67
#Mann= 3 , 0 , 0
       0      .1       0   472.3    .045       0   487.3      .1       0
Bank Sta=472.3,487.3
XS Rating Curve= 0 ,0
Exp/Cntr=0.3,0.1

Type RM Length L Ch R = 1 ,1516.1  ,288.6,280,271.5
XS GIS Cut Line= 2
     1928085.317      256274.458     1927676.199      257054.428
#Sta/Elev= 30
       0 2425.62      10 2422.13      20 2419.72      30 2418.34      40  2414.4
    70.1 2401.25   100.1 2385.43   110.1 2380.86   120.1 2377.31   130.1 2376.27
   150.1 2368.65   230.2 2343.37   240.2 2343.04   310.3 2322.45   320.3 2321.18
   337.9 2321.55   352.9 2322.52   410.4 2326.66   430.4 2330.65   450.4 2333.36
   470.4 2337.76   540.5 2354.77   560.5 2357.75   590.5 2366.28   650.6 2388.93
   660.6  2389.9   670.6 2393.15   680.6 2394.69   780.7 2398.54   880.8 2397.82
#Mann= 3 , 0 , 0
       0      .1       0   337.9    .045       0   352.9      .1       0
Bank Sta=337.9,352.9
XS Rating Curve= 0 ,0
Exp/Cntr=0.3,0.1

Type RM Length L Ch R = 1 ,1235.4  ,333.8,345,356.1
XS GIS Cut Line= 2
     1927708.938      256153.399     1927631.751      256876.942
#Sta/Elev= 30
       0 2409.14      10 2408.52    29.9 2404.53    49.8 2401.69    69.8 2394.84
   129.6 2372.04   139.6 2369.74   149.5  2368.5   159.5 2364.91   169.4 2360.88
   199.4 2346.43   209.3 2342.46   219.3 2339.37   229.3 2337.31   239.2 2336.62
   269.1 2329.83     299 2325.11   398.7 2316.58   418.6 2316.17   438.6 2316.96
   468.5 2322.86   508.4 2337.62   518.3  2337.7   598.1 2368.44     608 2368.92
   647.9 2383.54   657.9  2386.5   677.8 2389.77   687.8 2390.68   727.6 2392.51
#Mann= 3 , 0 , 0
       0      .1       0   398.7    .045       0   418.6      .1       0
Bank Sta=398.7,418.6
XS Rating Curve= 0 ,0
Exp/Cntr=0.3,0.1

Type RM Length L Ch R = 1 ,890.5   ,240,262.6,285.2
XS GIS Cut Line= 3
     1927614.743      256100.723     1927184.572      256712.788
     1927105.325       256845.81
#Sta/Elev= 30
       0  2396.3    69.8 2391.24    79.8 2389.99    89.8 2387.36   109.7 2379.17
   119.7 2378.22   149.6 2368.23   199.5 2355.06   219.4 2350.64   229.4 2350.31
   339.1 2321.76   349.1 2321.09     379 2314.84     389  2314.6     399  2314.6
   478.8  2318.2   528.7 2321.53   538.6 2322.85   558.6  2329.1   568.6 2330.66
   578.5 2333.46   618.4 2347.99   628.4 2350.96   638.4 2352.72   728.2 2357.78
   786.8 2362.74   806.2 2363.76   873.9 2372.16   893.3 2376.76     903 2377.64
#Mann= 3 , 0 , 0
       0      .1       0     379    .045       0     399      .1       0
#XS Ineff= 2 , 0
          236.64 2350.66
Permanent Ineff=
       F       F
Bank Sta=379,399
XS Rating Curve= 0 ,0
Exp/Cntr=0.3,0.1

Type RM Length L Ch R = 1 ,627.1   ,302.6,296.4,290.2
XS GIS Cut Line= 3
      1927519.47      256095.529     1927360.315       256273.28
     1926906.014      256265.344
#Sta/Elev= 30
       0 2377.14    59.6 2371.06    69.6 2368.83    99.4 2365.46   129.2  2359.4
   139.2 2358.09   178.9 2348.68   188.9 2344.62   198.8 2341.44   238.6 2330.44
   258.4 2328.03     288  2326.1   337.4 2329.08   357.1 2327.84     367 2320.27
   376.9 2315.86   387.4 2314.59   402.4  2314.5   436.1 2314.46   465.8 2319.67
   485.5 2324.83     525 2337.85   534.9 2343.06   544.8 2346.81   564.6 2351.48
   574.4 2352.84   584.3 2353.39   663.3 2353.96   683.1 2356.41     693 2358.31
#Mann= 3 , 0 , 0
       0      .1       0   387.4    .045       0   402.4      .1       0
Bank Sta=387.4,402.4
XS Rating Curve= 0 ,0
Exp/Cntr=0.3,0.1

Type RM Length L Ch R = 1 ,330.7   ,72.1,74.5,76.8
XS GIS Cut Line= 2
     1927544.343       255877.55     1926751.257      256081.949
#Sta/Elev= 30
       0 2366.68    69.9 2357.49    89.9 2352.36   129.8 2344.78   139.8 2344.31
   149.8 2345.12   169.8 2349.22   199.8 2351.88   239.7 2352.37   259.7 2348.77
   319.6 2334.69   339.6 2325.89   379.5 2317.39   399.5 2309.89   404.6 2308.86
   409.5 2307.88   419.6 2308.41   449.4  2309.5   489.4 2316.04   499.4 2319.69
   529.4  2327.8   569.3 2342.17   579.3 2347.32   599.3 2352.41   649.2 2358.62
   669.2 2362.86   689.2 2365.72   729.1 2369.85   769.1 2372.26     819 2372.55
#Mann= 3 , 0 , 0
       0      .1       0   404.6    .045       0   419.6      .1       0
Bank Sta=404.6,419.6
XS Rating Curve= 0 ,0
Exp/Cntr=0.3,0.1

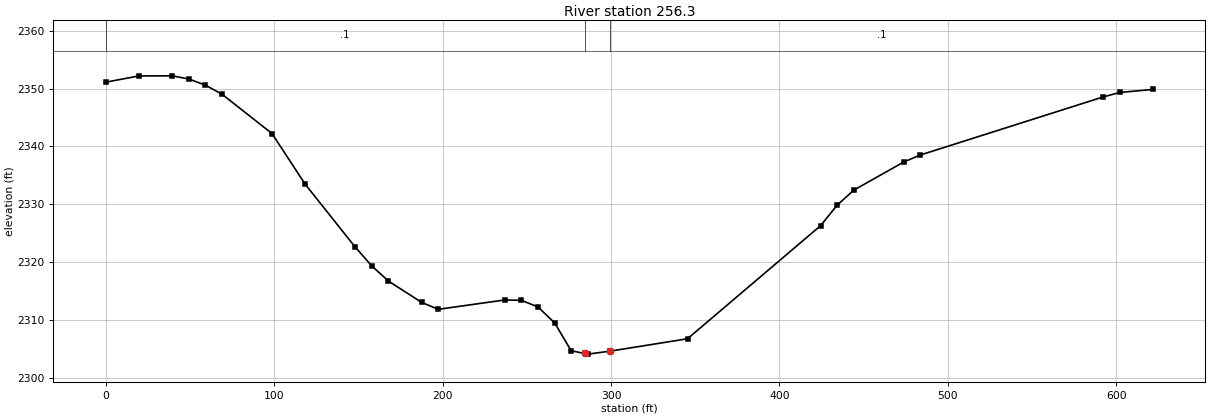
Type RM Length L Ch R = 1 ,256.3   ,261.6,256.2,250.9
XS GIS Cut Line= 2
     1927413.335      255865.683      1926798.42      255957.621
#Sta/Elev= 30
       0 2351.12    19.7  2352.2    39.5 2352.22    49.4 2351.66    59.2  2350.6
    69.1 2349.02    98.7 2342.23   118.4 2333.47     148 2322.63   157.9 2319.35
   167.8 2316.72   187.5 2313.04   197.4 2311.83   236.9 2313.45   246.7 2313.39
   256.6 2312.24   266.5 2309.49   276.3 2304.67   284.3 2304.19   286.2 2304.08
   299.3 2304.59   345.4 2306.74   424.4  2326.3   434.2 2329.84   444.1 2332.44
   473.7  2337.3   483.6 2338.52   592.1 2348.56     602 2349.34   621.8 2349.87
#Mann= 3 , 0 , 0
       0      .1       0   284.3    .045       0   299.3      .1       0
Bank Sta=284.3,299.3
XS Rating Curve= 0 ,0
Exp/Cntr=0.3,0.1

Chan Stop Cuts=-1
Use User Specified Reach Order=0
Composite Channel Slope=5